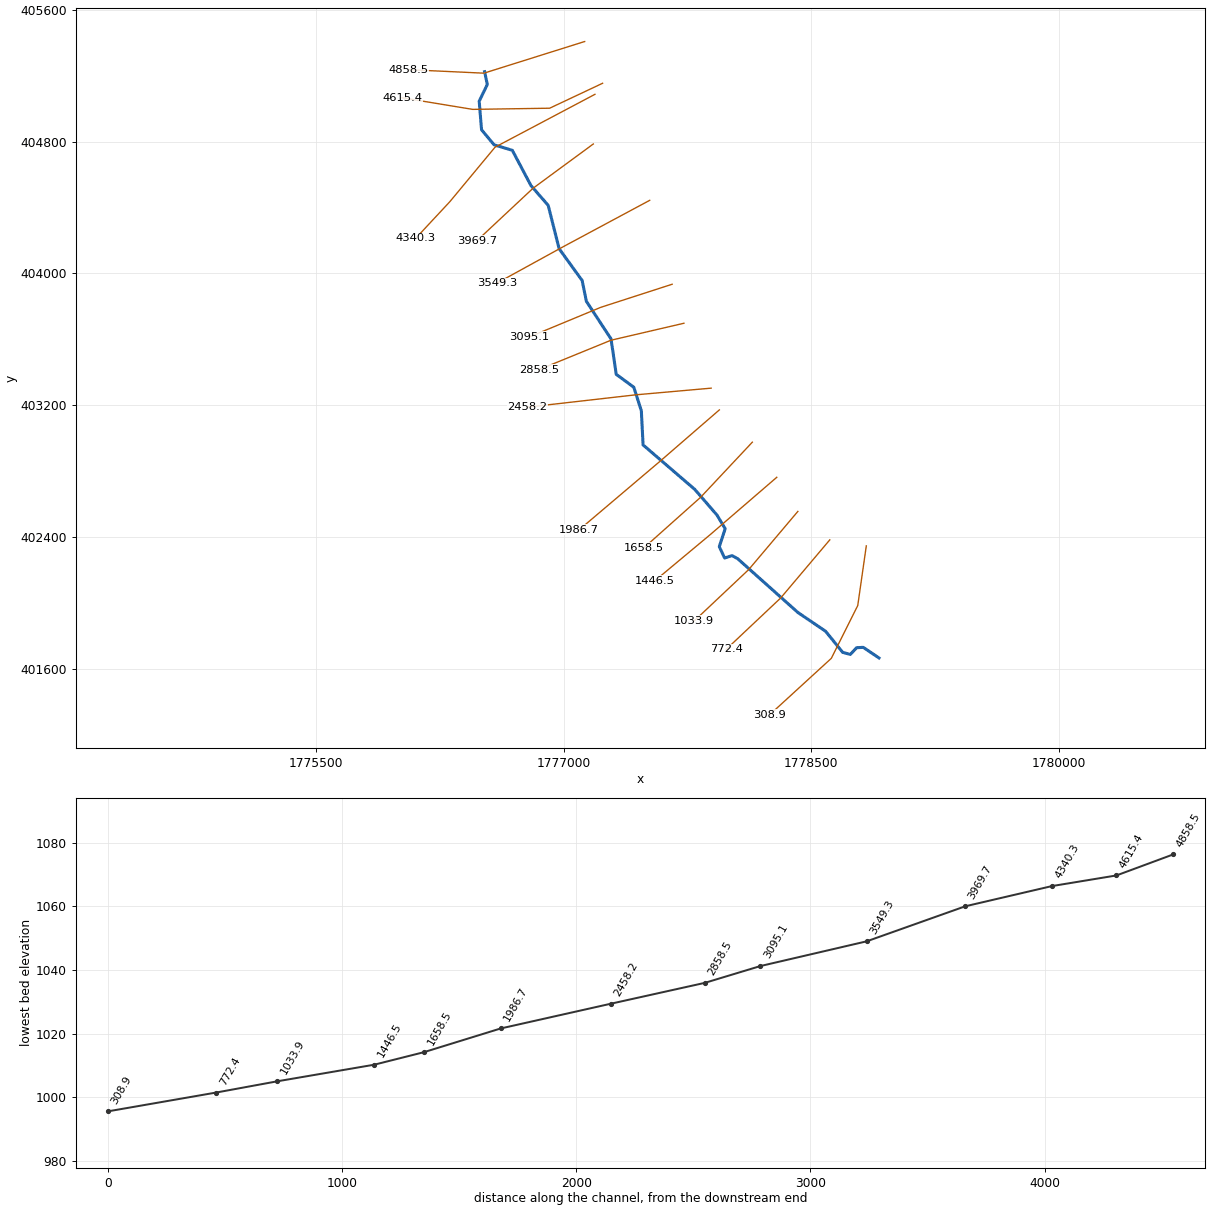
--- TrbLPPC.prj (project) ---

Proj Title=TrbLPPC
Current Plan=p01
Geom File=g01
Flow File=f01
Plan File=p01
DSS Export Rating Curves=0
DSS Export Rating Curve Sorted=0
DSS Export Volume Flow Curves=0
DXF OffsetX=0
DXF OffsetY=0
DXF ScaleX=0
DXF ScaleY=0

--- TrbLPPC.p01 (plan) ---

Plan Title=Floodplain
Program Version=4.00
Geom File=g01
Flow File=f01
K Sum by GR=0
Std Step Tol=0.01
Critical Tol=0.01
Num of Std Step Trials=20
Max Error Tol=0.3
Flow Tol Ratio=0.001
Split Flow NTrial=30
Split Flow Tol=0.02
Split Flow Ratio=0.02
Log Output Level=0
Friction Slope Method=1
Unsteady Friction Slope Method=2
Unsteady Bridges Friction Slope Method=1
Global Log Level=0
CheckData=False
Run HTab=0
Run UNet=0
Run PostProcess=0
UNET Theta=0
UNET Theta Warmup=0
UNET ZTol=0
UNET ZSATol=0
UNET MxIter=0
UNET MaxInSteps=0
UNET DtIC=0
UNET DtMin=0
UNET MaxCRTS=0
UNET WFStab=0
UNET SFStab=0
UNET WFX=0
UNET SFX=0
UNET DSS MLevel=0
UNET DZMax Abort=0
UNET Convert EG Bridges=0
UNET Use Existing IB Tables=0
UNET Froude Limit=0
UNET Froude Power=0
Write IC File=0
Echo Input=False
Echo Output=False
Write Detailed=0

--- TrbLPPC.f01 (steady flow) ---

Flow Title=NFF Regression Equation
Program Version=4.00
Number of Profiles=1
Profile Names=P100yr
River Rch & RM=TrbLPPC,Main      ,4858.5
324.3630
River Rch & RM=TrbLPPC,Main      ,4340.3
331.7167
River Rch & RM=TrbLPPC,Main      ,3969.7
399.9899
River Rch & RM=TrbLPPC,Main      ,3549.3
418.9487
River Rch & RM=TrbLPPC,Main      ,1986.7
461.0662
River Rch & RM=TrbLPPC,Main      ,1658.5
543.5229
River Rch & RM=TrbLPPC,Main      ,308.9
579.1800
Boundary for River Rch & Prof#=TrbLPPC,Main      ,1
Up Type=0
Dn Type=3
Dn Slope=0.013808

--- TrbLPPC.g01 (geometry) ---

Geom Title=USGS 3m DEM
Program Version=4.00

River Reach=TrbLPPC     ,Main
Reach XY= 30
     1776521.521      405223.374     1776538.080      405146.066
     1776488.897      405044.343     1776503.075      404871.246
     1776578.710      404780.178     1776689.542      404746.486
     1776802.223      404532.831     1776906.454      404413.092
     1776972.806      404149.839     1777111.914      403957.296
     1777137.740      403830.946     1777286.834      403603.217
     1777318.603      403388.099     1777424.622      403310.238
     1777470.401      403167.618     1777480.974      402960.049
     1777793.716      402690.788     1777928.201      402534.982
     1777977.978      402452.112     1777942.299      402343.385
     1777974.609      402274.386     1778019.877      402289.127
     1778053.603      402270.189     1778418.222      401944.002
     1778585.673      401830.452     1778689.388      401702.298
     1778735.444      401689.679     1778773.539      401730.489
     1778813.661      401732.814     1778909.304      401668.165

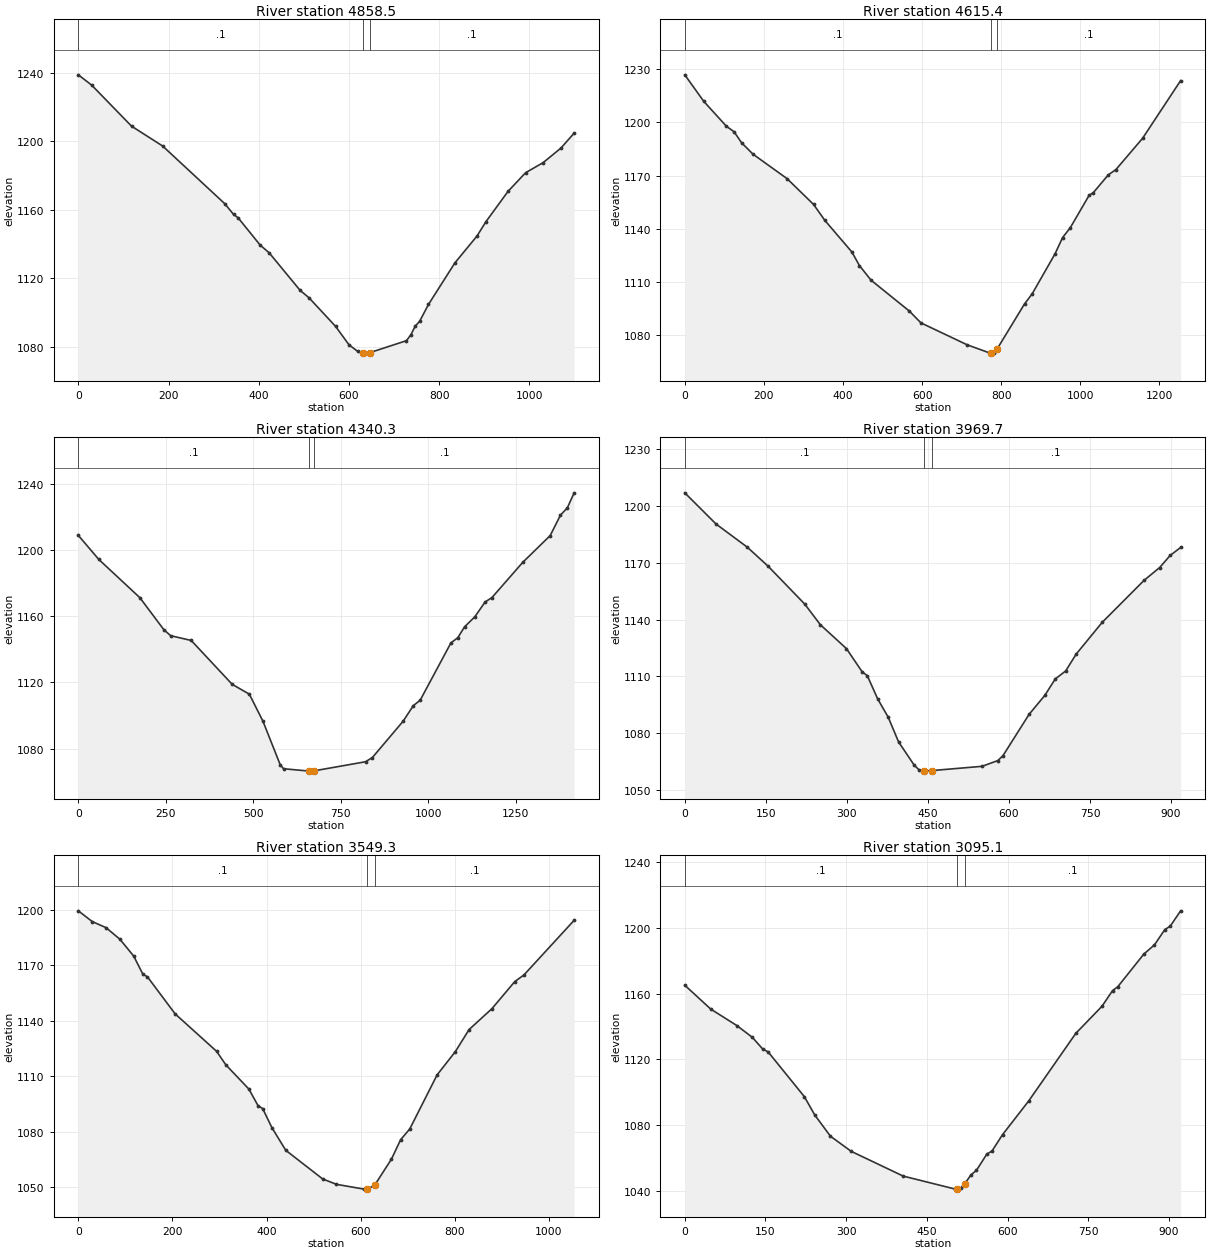
Type RM Length L Ch R = 1 ,4858.5,249.089,243.17,244.293
XS GIS Cut Line= 3
     1777127.419      405406.301     1776517.503      405214.414
     1776058.039      405235.820
#Sta/Elev= 30
       0 1238.73    29.5 1232.74   118.0 1208.77   186.9 1197.19   324.6 1163.54
   344.3 1157.22   354.1 1155.35   403.3 1139.32   423.0 1134.90   491.8 1112.93
   511.5 1108.60   570.5 1091.89   600.0 1081.21   619.7 1077.26   631.9 1076.44
   639.4 1076.30   646.9 1076.64   727.5 1083.56   737.3 1086.98   747.0 1092.05
   756.8 1094.88   776.4 1104.72   835.1 1129.02   884.0 1144.65   903.6 1152.94
   952.6 1170.65   991.7 1181.60  1030.8 1187.51  1070.0 1195.96  1099.4 1204.71
#Mann= 3 , 0 , 0
       0     0.1       0   631.9   0.045       0   646.9     0.1       0
Bank Sta=   631.9,   646.9
Exp/Cntr=0.3,0.1

Type RM Length L Ch R = 1 ,4615.4,268.929,275.105,287.441
XS GIS Cut Line= 4
     1777235.907      405153.162     1776915.474      405001.945
     1776449.322      404994.877     1776021.876      405065.339
#Sta/Elev= 30
       0 1226.87    47.9 1211.91   105.3 1197.80   124.5 1194.73   143.6 1188.50
   172.4 1182.06   258.6 1168.23   325.6 1153.66   354.3 1144.60   422.3 1126.85
   441.7 1119.09   470.9 1110.88   568.0 1093.38   597.1 1086.75   713.7 1074.40
   772.0 1069.67   775.1 1069.68   781.7 1069.70   790.1 1072.16   859.0 1097.46
   878.3 1103.15   936.1 1125.74   955.3 1134.97   974.6 1140.47  1022.7 1158.95
  1032.3 1160.14  1070.8 1170.36  1090.1 1173.36  1157.5 1191.01  1253.7 1223.61
#Mann= 3 , 0 , 0
       0     0.1       0   775.1   0.045       0   790.1     0.1       0
Bank Sta=   775.1,   790.1
Exp/Cntr=0.3,0.1

Type RM Length L Ch R = 1 ,4340.3,363.5,370.599,371.013
XS GIS Cut Line= 4
     1777189.412      405086.003     1776584.980      404765.706
     1776311.177      404435.076     1776104.533      404212.934
#Sta/Elev= 30
       0 1208.96    58.6 1194.39   175.9 1171.25   244.3 1151.90   263.8 1148.28
   322.5 1145.39   439.7 1118.83   488.6 1112.90   527.7 1096.44   576.6 1070.30
   586.3 1067.78   659.4 1066.35   664.5 1066.33   674.4 1066.53   820.6 1072.00
   840.2 1074.56   928.0 1096.53   957.2 1105.96   976.7 1109.23  1064.6 1143.92
  1084.1 1147.03  1103.6 1153.65  1132.9 1159.71  1162.3 1168.67  1181.8 1171.34
  1269.9 1192.67  1348.2 1208.84  1377.6 1221.22  1397.2 1225.62  1416.7 1234.71
#Mann= 3 , 0 , 0
       0     0.1       0   659.4   0.045       0   674.4     0.1       0
Bank Sta=   659.4,   674.4
Exp/Cntr=0.3,0.1

Type RM Length L Ch R = 1 ,3969.7,423.29,420.4,415.04
XS GIS Cut Line= 3
     1777179.580      404785.059     1776814.363      404516.128
     1776475.593      404198.859
#Sta/Elev= 30
       0 1207.06    57.9 1190.56   115.8 1178.31   154.4 1168.22   222.0 1148.26
   250.9 1137.35   299.2 1124.72   328.1 1112.54   337.8 1110.41   357.1 1098.08
   376.4 1088.52   395.7 1075.40   424.6 1063.14   434.3 1060.44   442.3 1060.05
   443.9 1059.97   457.3 1060.26   550.2 1062.51   579.3 1065.54   588.9 1068.15
   637.3 1090.01   666.3 1099.97   685.6 1108.67   705.0 1112.92   724.3 1121.79
   772.6 1138.62   850.0 1160.79   879.0 1167.59   898.3 1173.97   917.7 1178.17
#Mann= 3 , 0 , 0
       0     0.1       0   442.3   0.045       0   457.3     0.1       0
Bank Sta=   442.3,   457.3
Exp/Cntr=0.3,0.1

Type RM Length L Ch R = 1 ,3549.3,452.335,454.128,448.089
XS GIS Cut Line= 3
     1777521.210      404443.418     1776994.716      404160.556
     1776594.882      403940.600
#Sta/Elev= 30
       0 1199.39    29.4 1193.61    58.8 1190.30    88.2 1184.08   117.6 1174.97
   137.2 1165.15   147.0 1163.69   205.8 1143.69   293.9 1123.47   313.5 1116.17
   362.5 1103.06   382.1 1094.04   391.9 1092.49   411.5 1082.19   440.9 1069.97
   519.3 1054.49   548.7 1051.56   607.4 1048.97   614.6 1049.00   629.6 1050.97
   665.6 1065.18   685.1 1075.68   704.5 1081.48   762.7 1110.73   801.6 1123.35
   830.7 1135.24   879.2 1146.50   927.8 1161.16   947.2 1164.71  1054.0 1194.28
#Mann= 3 , 0 , 0
       0     0.1       0   614.6   0.045       0   629.6     0.1       0
Bank Sta=   614.6,   629.6
Exp/Cntr=0.3,0.1

Type RM Length L Ch R = 1 ,3095.1,233.224,236.597,237.51
XS GIS Cut Line= 3
     1777656.890      403934.466     1777224.638      403794.450
     1776793.078      403615.248
#Sta/Elev= 30
       0 1165.04    48.3 1150.53    96.7 1140.56   125.7 1133.35   145.0 1126.22
   154.7 1124.63   222.3 1097.34   241.7 1086.17   270.7 1073.34   309.4 1064.13
   406.0 1049.11   503.0 1041.19   505.3 1041.34   512.8 1041.85   520.3 1044.42
   532.2 1049.94   542.0 1052.53   561.4 1062.44   571.2 1064.39   590.7 1074.30
   639.3 1094.75   726.9 1135.83   775.6 1152.29   795.1 1161.75   804.8 1164.10
   853.5 1184.03   873.0 1189.52   892.4 1198.86   902.2 1200.84   921.7 1210.23
#Mann= 3 , 0 , 0
       0     0.1       0   505.3   0.045       0   520.3     0.1       0
Bank Sta=   505.3,   520.3
Exp/Cntr=0.3,0.1

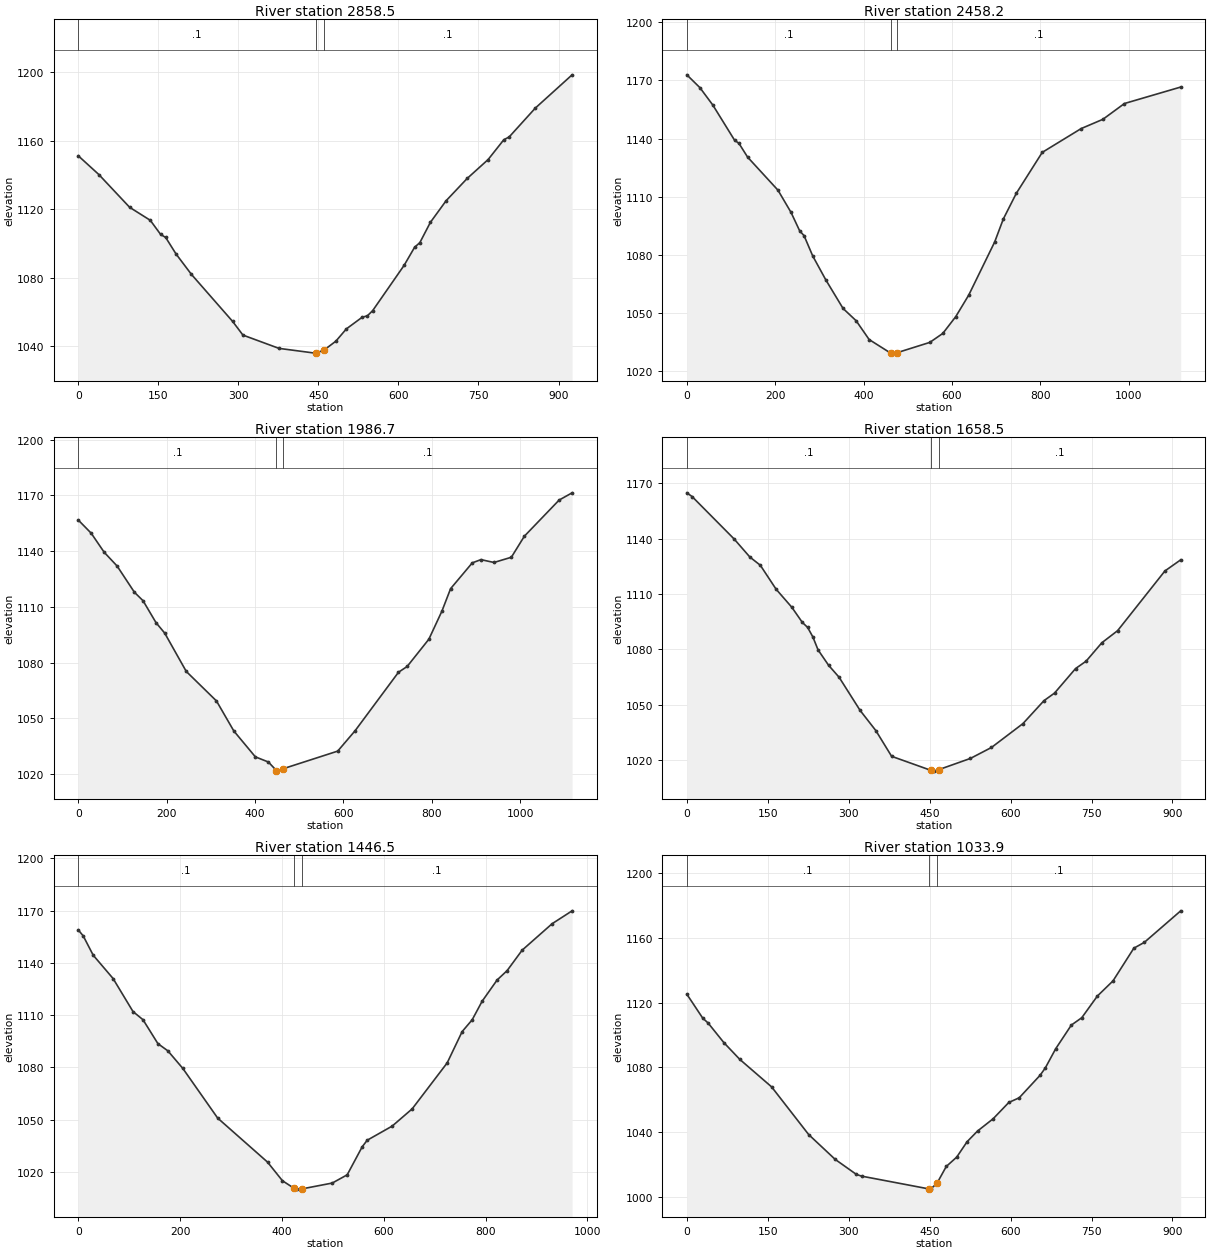
Type RM Length L Ch R = 1 ,2858.5,400.454,400.289,393.632
XS GIS Cut Line= 3
     1777728.202      403697.962     1777286.816      403595.046
     1776849.786      403416.293
#Sta/Elev= 30
       0 1151.21    38.6 1140.25    96.4 1121.08   135.0 1113.51   154.3 1105.30
   163.9 1103.47   183.2 1093.87   212.1 1081.92   289.3 1054.44   308.6 1046.46
   376.1 1038.70   443.6 1035.92   445.7 1036.01   460.7 1037.74   482.7 1042.89
   502.4 1050.07   531.9 1056.85   541.8 1057.72   551.6 1060.70   610.6 1087.19
   630.3 1097.77   640.1 1100.46   659.8 1112.29   689.3 1124.94   728.7 1137.93
   768.0 1148.99   797.5 1160.60   807.4 1162.18   856.5 1179.07   925.4 1198.49
#Mann= 3 , 0 , 0
       0     0.1       0   445.7   0.045       0   460.7     0.1       0
Bank Sta=   445.7,   460.7
Exp/Cntr=0.3,0.1

Type RM Length L Ch R = 1 ,2458.2,451.174,471.585,482.711
XS GIS Cut Line= 3
     1777893.046      403304.488     1777433.292      403263.617
     1776781.578      403189.187
#Sta/Elev= 30
       0 1172.88    29.5 1166.28    58.9 1157.25   108.0 1139.16   117.8 1137.57
   137.5 1130.44   206.2 1113.39   235.7 1101.96   255.3 1092.43   265.2 1089.96
   284.8 1079.50   314.3 1067.20   353.5 1052.40   383.0 1046.10   412.5 1036.38
   460.9 1029.43   461.6 1029.38   475.9 1029.62   549.7 1034.91   579.1 1039.53
   608.4 1048.18   637.8 1059.29   696.5 1086.68   716.1 1098.55   745.5 1111.79
   804.2 1132.90   892.3 1145.17   941.3 1149.93   990.2 1158.09  1117.5 1166.58
#Mann= 3 , 0 , 0
       0     0.1       0   460.9   0.045       0   475.9     0.1       0
Bank Sta=   460.9,   475.9
Exp/Cntr=0.3,0.1

Type RM Length L Ch R = 1 ,1986.7,325.879,328.107,328.446
XS GIS Cut Line= 3
     1777942.614      403172.498     1777580.600      402858.557
     1777093.840      402445.270
#Sta/Elev= 30
       0 1156.73    29.3 1149.63    58.7 1139.37    88.0 1131.95   127.1 1117.85
   146.7 1113.28   176.0 1101.49   195.6 1095.89   244.5 1075.23   312.9 1059.33
   352.1 1043.20   400.9 1029.25   430.3 1026.49   448.5 1021.91   449.8 1021.58
   463.5 1022.85   587.2 1032.35   626.5 1043.29   724.8 1074.80   744.4 1077.90
   793.5 1092.56   823.0 1107.65   842.7 1119.77   891.8 1133.67   911.4 1135.40
   940.9 1133.87   980.2 1136.68  1009.7 1148.02  1088.3 1167.45  1117.7 1171.35
#Mann= 3 , 0 , 0
       0     0.1       0   448.5   0.045       0   463.5     0.1       0
Bank Sta=   448.5,   463.5
Exp/Cntr=0.3,0.1

Type RM Length L Ch R = 1 ,1658.5,214.216,212.013,211.698
XS GIS Cut Line= 3
     1778142.308      402976.817     1777829.653      402643.104
     1777488.150      402337.965
#Sta/Elev= 30
       0 1164.72     9.7 1162.71    87.6 1139.75   116.8 1129.97   136.2 1125.51
   165.4 1112.57   194.6 1102.77   214.1 1094.57   223.8 1091.91   233.5 1086.76
   243.2 1079.72   262.7 1071.40   282.2 1064.91   321.1 1046.98   350.3 1036.04
   379.5 1022.14   451.9 1014.59   457.3 1014.12   466.9 1014.92   525.5 1020.99
   564.5 1026.91   622.9 1039.84   661.9 1052.26   681.4 1056.34   720.4 1069.62
   739.9 1073.61   769.1 1083.58   798.3 1090.12   886.0 1122.44   915.3 1128.47
#Mann= 3 , 0 , 0
       0     0.1       0   451.9   0.045       0   466.9     0.1       0
Bank Sta=   451.9,   466.9
Exp/Cntr=0.3,0.1

Type RM Length L Ch R = 1 ,1446.5,408.322,412.621,414.954
XS GIS Cut Line= 3
     1778290.249      402763.883     1777890.309      402418.700
     1777551.252      402135.444
#Sta/Elev= 30
       0 1158.97     9.8 1155.52    29.4 1144.44    68.5 1131.04   107.6 1112.09
   127.2 1107.42   156.5 1093.69   176.1 1089.54   205.5 1079.44   273.9 1050.96
   371.8 1025.71   401.1 1015.01   424.3 1010.60   430.5 1010.19   439.3 1010.32
   499.0 1013.68   528.3 1018.40   557.8 1034.50   567.6 1038.25   616.7 1046.37
   655.9 1056.24   724.7 1082.63   754.1 1100.60   773.8 1107.37   793.4 1118.04
   822.8 1130.22   842.5 1135.61   871.9 1147.31   930.8 1162.50   970.1 1169.91
#Mann= 3 , 0 , 0
       0     0.1       0   424.3   0.045       0   439.3     0.1       0
Bank Sta=   424.3,   439.3
Exp/Cntr=0.3,0.1

Type RM Length L Ch R = 1 ,1033.9,261.602,261.513,262.085
XS GIS Cut Line= 3
     1778417.877      402557.016     1778120.327      402204.257
     1777790.317      401892.685
#Sta/Elev= 30
       0 1125.15    29.5 1110.36    39.3 1107.43    68.7 1095.27    98.2 1084.95
   157.1 1068.02   225.8 1038.62   274.9 1023.33   314.2 1014.06   324.0 1012.99
   448.6 1005.12   451.7 1004.99   463.6 1008.61   480.8 1018.96   500.1 1024.71
   519.4 1034.22   538.7 1040.79   567.7 1048.38   596.7 1058.42   616.0 1061.30
   654.6 1075.15   664.3 1079.67   683.6 1091.54   712.6 1106.12   731.9 1110.65
   760.8 1124.00   789.8 1133.36   828.4 1153.51   847.8 1157.09   915.3 1176.55
#Mann= 3 , 0 , 0
       0     0.1       0   448.6   0.045       0   463.6     0.1       0
Bank Sta=   448.6,   463.6
Exp/Cntr=0.3,0.1

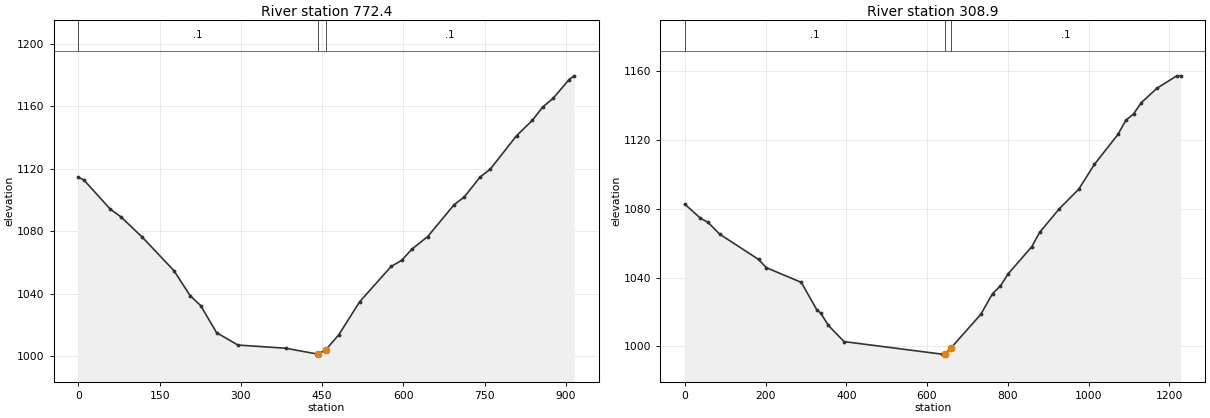
Type RM Length L Ch R = 1 ,772.4,457.754,463.497,470.332
XS GIS Cut Line= 3
     1778611.236      402384.551     1778313.686      402031.792
     1777983.677      401720.220
#Sta/Elev= 30
       0 1114.51     9.8 1112.98    58.9 1094.20    78.6 1089.23   117.8 1076.33
   176.7 1054.77   206.2 1038.93   225.8 1032.49   255.3 1015.14   294.6 1007.26
   382.9 1005.22   441.7 1001.47   441.9 1001.45   456.7 1004.16   480.8 1013.84
   519.4 1034.96   577.4 1057.50   596.7 1061.39   616.0 1068.66   645.0 1076.67
   693.2 1096.81   712.6 1102.03   741.5 1114.61   760.8 1119.91   809.1 1141.19
   838.1 1150.94   857.4 1159.55   876.7 1165.14   905.7 1176.94   915.3 1179.43
#Mann= 3 , 0 , 0
       0     0.1       0   441.7   0.045       0   456.7     0.1       0
Bank Sta=   441.7,   456.7
Exp/Cntr=0.3,0.1

Type RM Length L Ch R = 1 ,308.9,309.961,308.905,308.061
XS GIS Cut Line= 4
     1778832.229      402347.975     1778780.568      401986.349
     1778620.419      401666.051     1778248.461      401325.090
#Sta/Elev= 30
       0 1082.75    38.5 1074.59    57.7 1072.09    86.5 1065.26   182.6 1050.61
   201.9 1045.81   288.4 1037.25   326.8 1021.38   336.5 1019.42   355.7 1012.21
   394.3 1002.81   636.3  995.52   643.9  995.63   658.9  999.04   733.1 1018.65
   762.2 1030.72   781.6 1035.13   801.0 1042.25   859.3 1057.97   878.7 1066.27
   927.2 1079.96   975.7 1091.45  1014.5 1105.87  1072.7 1123.24  1092.1 1131.42
  1111.5 1135.23  1131.0 1141.83  1169.8 1150.20  1218.3 1157.31  1228.0 1157.34
#Mann= 3 , 0 , 0
       0     0.1       0   643.9   0.045       0   658.9     0.1       0
Bank Sta=   643.9,   658.9
Exp/Cntr=0.3,0.1